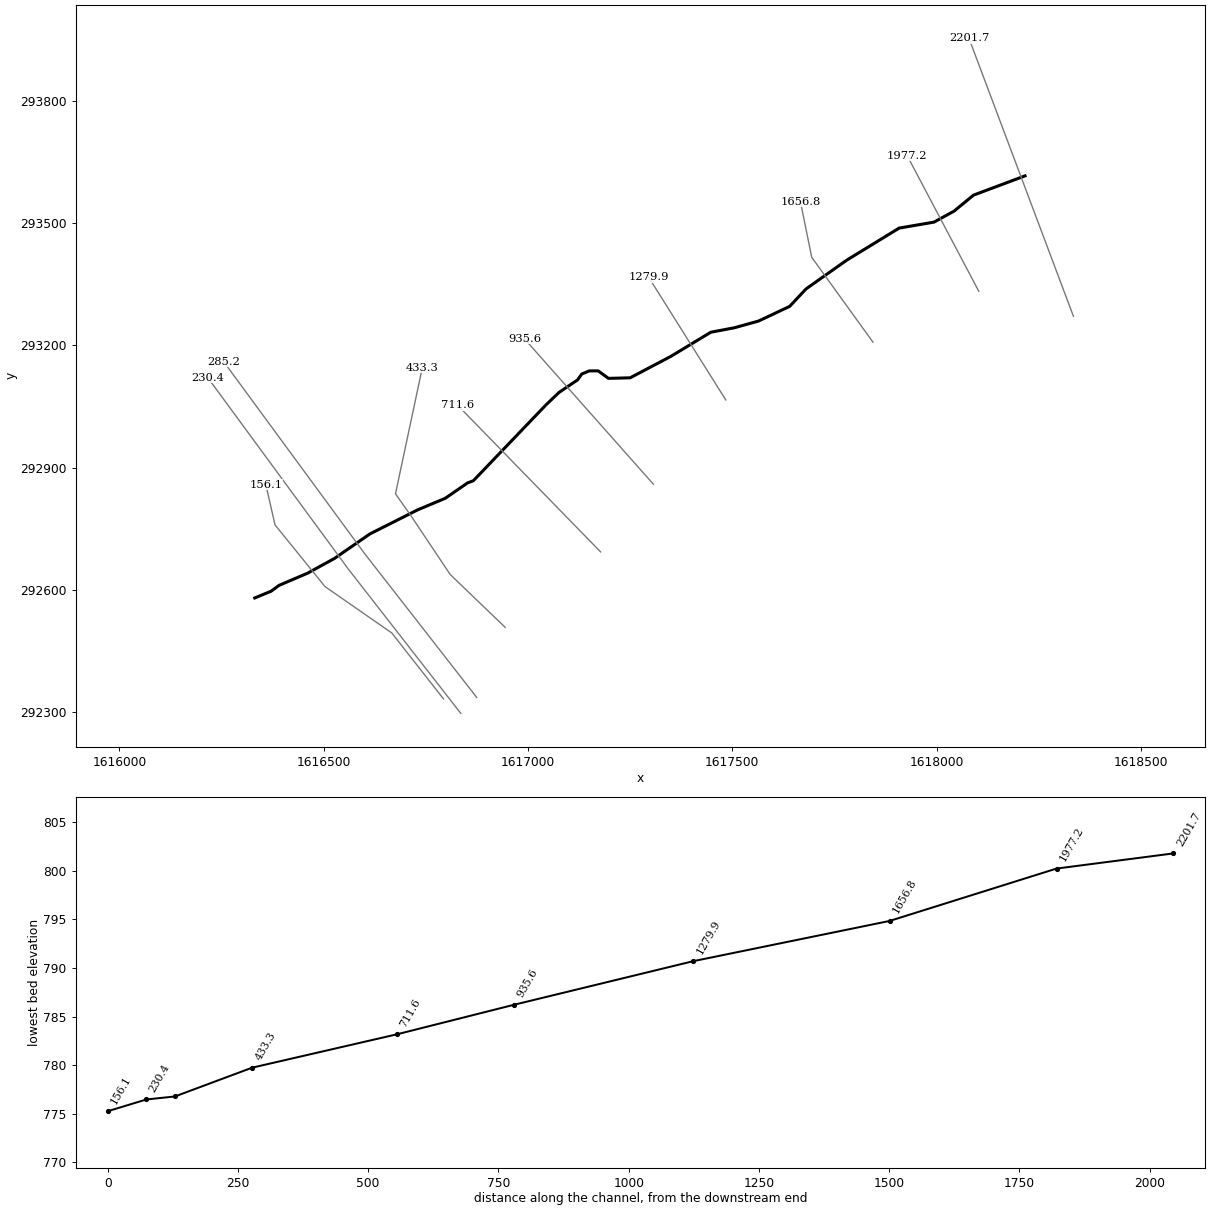
--- JOCKYCPRN.prj (project) ---

Proj Title=JOCKYCPRN
Current Plan=p01
Geom File=g01
Flow File=f01
Plan File=p01
DSS Export Rating Curves=0
DSS Export Rating Curve Sorted=0
DSS Export Volume Flow Curves=0
DXF OffsetX=0
DXF OffsetY=0
DXF ScaleX=0
DXF ScaleY=0

--- JOCKYCPRN.p01 (plan) ---

Plan Title=Floodplain
Program Version=4.00
Geom File=g01
Flow File=f01
K Sum by GR=0
Std Step Tol=0.01
Critical Tol=0.01
Num of Std Step Trials=20
Max Error Tol=0.3
Flow Tol Ratio=0.001
Split Flow NTrial=30
Split Flow Tol=0.02
Split Flow Ratio=0.02
Log Output Level=0
Friction Slope Method=1
Unsteady Friction Slope Method=2
Unsteady Bridges Friction Slope Method=1
Global Log Level=0
CheckData=False
Run HTab=0
Run UNet=0
Run PostProcess=0
UNET Theta=0
UNET Theta Warmup=0
UNET ZTol=0
UNET ZSATol=0
UNET MxIter=0
UNET MaxInSteps=0
UNET DtIC=0
UNET DtMin=0
UNET MaxCRTS=0
UNET WFStab=0
UNET SFStab=0
UNET WFX=0
UNET SFX=0
UNET DSS MLevel=0
UNET DZMax Abort=0
UNET Convert EG Bridges=0
UNET Use Existing IB Tables=0
UNET Froude Limit=0
UNET Froude Power=0
Write IC File=0
Echo Input=False
Echo Output=False
Write Detailed=0

--- JOCKYCPRN.f01 (steady flow) ---

Flow Title=NFF Regression Equation
Program Version=4.10
Number of Profiles= 1
Profile Names=P100yr
River Rch & RM=JOCKYCPRN,Main            ,2201.7
751.3862
River Rch & RM=JOCKYCPRN,Main            ,433.3
814.2409
River Rch & RM=JOCKYCPRN,Main            ,285.2
818.6862
Boundary for River Rch & Prof#=JOCKYCPRN,Main            , 1
Up Type= 0
Dn Type= 3
Dn Slope=0.0163
DSS Import GetInterval= 0
DSS Import GetPeak= 0
DSS Import FillOption= 0

--- JOCKYCPRN.g01 (geometry) ---

Geom Title=USGS 10m DEM
Program Version=4.10

River Reach=JOCKYCPRN       ,Main
Reach XY= 30
     1618216.456      293615.925     1618090.423      293568.663
     1618042.573      293529.303      1617993.77      293502.462
     1617908.366      293487.821     1617779.777      293408.932
     1617680.445      293338.571     1617640.436      293295.803
     1617564.557      293259.933     1617505.233      293243.377
     1617447.289       293232.34     1617349.336      293173.017
     1617250.004      293120.591      1617196.91       293119.23
     1617171.817      293137.567     1617150.116      293137.567
      1617131.67      293129.972     1617121.274      293115.419
     1617075.896      293084.721     1617044.164       293054.37
     1616866.193      292868.121     1616851.987      292862.768
     1616797.468      292825.067     1616730.194      292796.855
      1616613.14       292737.73     1616526.201      292677.498
     1616461.097       292641.69     1616390.853      292611.586
     1616371.186      292597.163     1616331.177      292580.608

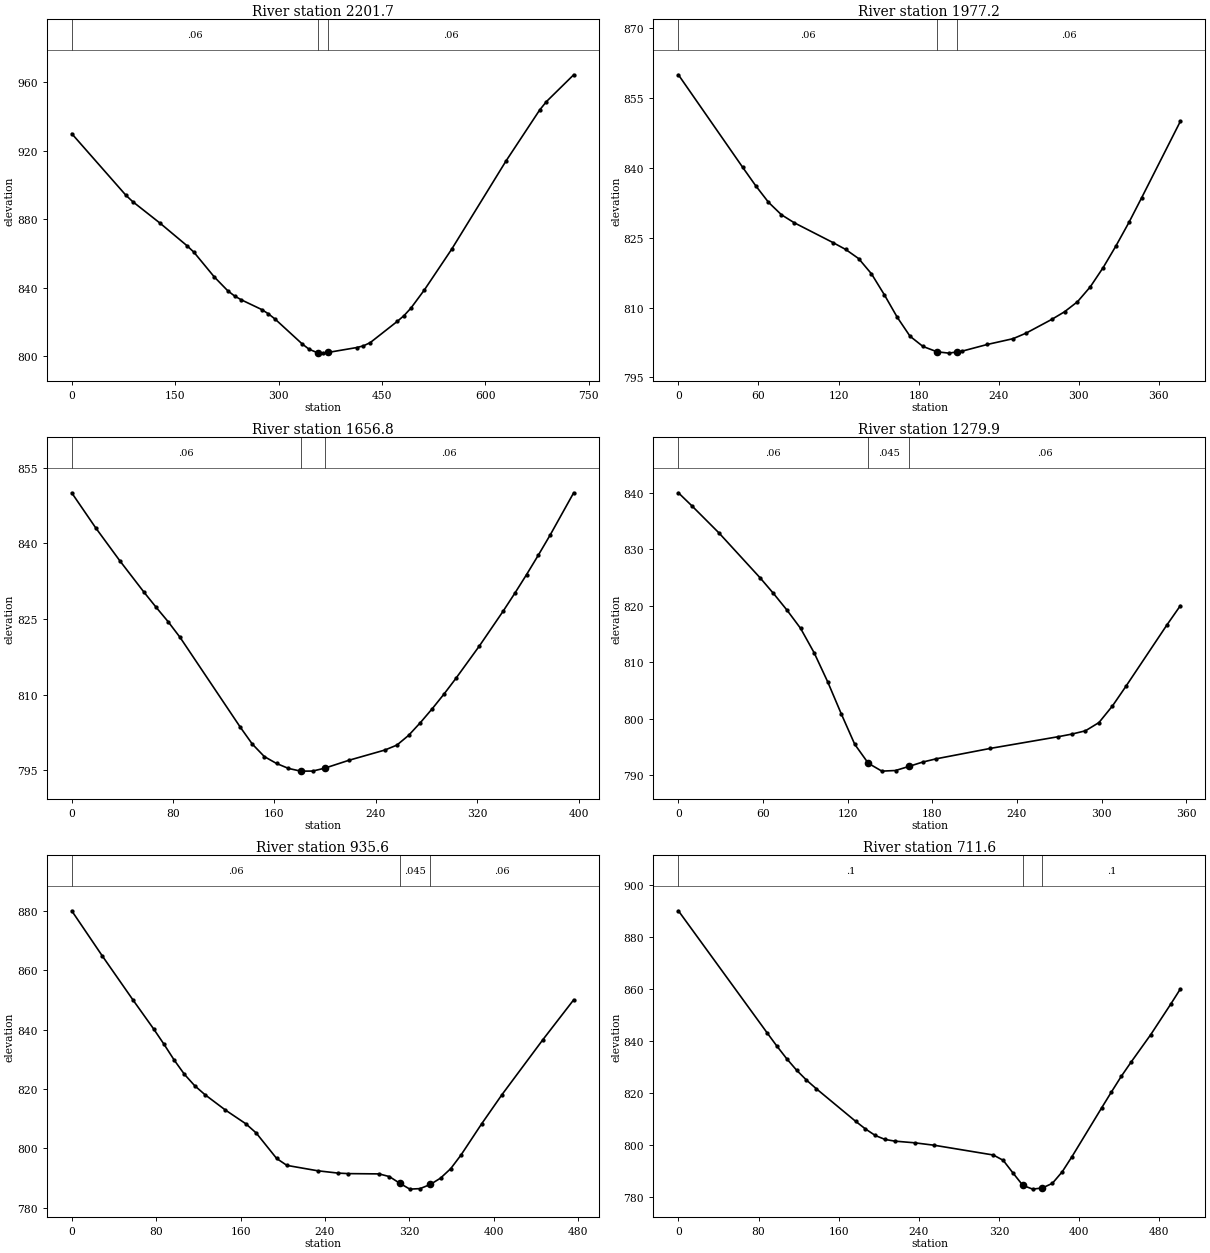
Type RM Length L Ch R = 1 ,2201.7  ,221.5,224.4,227.3
XS GIS Cut Line= 2
     1618334.901       293271.59     1618079.283      293953.238
#Sta/Elev= 30
       0  930.02    78.7  893.96    88.5  890.28   127.9  877.78   167.2  864.54
   177.1   860.8   206.6  846.37   226.3  838.22   236.1   835.2     246  832.92
   275.5  827.26   285.3  824.74   295.1  821.62   334.5  807.07   344.3  804.06
   356.5  801.98     364  801.79   371.5  802.17   413.2  805.04     423  806.03
   432.9  807.92   472.2  820.35     482  823.73   491.9  828.06   511.6  838.79
   550.9   862.4   629.6  913.88   678.8  943.91   688.6   948.8     728   964.4
#Mann= 3 , 0 , 0
       0     .06       0   356.5    .045       0   371.5     .06       0
Bank Sta=356.5,371.5
XS Rating Curve= 0 ,0
Exp/Cntr=0.3,0.1

Type RM Length L Ch R = 1 ,1977.2  ,317.2,320.4,323.5
XS GIS Cut Line= 2
     1618103.231      293332.939     1617927.842      293665.807
#Sta/Elev= 30
       0     860    48.2  840.12    57.9  836.19    67.5  832.63    77.2  829.95
    86.8  828.23   115.8  823.98   125.4  822.49   135.1  820.53   144.7  817.26
   154.4  812.74     164  807.94   173.6  803.86   183.3  801.66   193.8  800.52
   202.6  800.23   208.8  800.48   212.2  800.62   231.5  802.09   250.8  803.33
   260.5  804.51   279.8  807.47   289.4  809.11   299.1  811.26   308.7  814.46
   318.4  818.62     328  823.28   337.7  828.31   347.3  833.65   376.2     850
#Mann= 3 , 0 , 0
       0     .06       0   193.8    .045       0   208.8     .06       0
Bank Sta=193.8,208.8
XS Rating Curve= 0 ,0
Exp/Cntr=0.3,0.1

Type RM Length L Ch R = 1 ,1656.8  ,378.3,376.9,375.4
XS GIS Cut Line= 3
     1617844.337      293207.979     1617694.424      293416.206
     1617666.662      293552.975
#Sta/Elev= 30
       0  849.99      19  843.02      38  836.51      57  830.31    66.5  827.34
      76  824.48    85.5  821.34     133  803.55   142.5   800.2     152  797.72
   161.6  796.36     171  795.38   180.6  794.84   190.1  794.85   199.6  795.42
   218.6  796.98   247.1  799.02   256.6     800   265.9  801.94   275.2  804.47
   284.5  807.21   293.8  810.12   303.1   813.2   321.7  819.65   340.3  826.49
   349.6  830.07   358.9  833.78   368.2  837.64   377.5  841.61   396.1     850
#Mann= 3 , 0 , 0
       0     .06       0   180.6    .045       0   199.6     .06       0
Bank Sta=180.6,199.6
XS Rating Curve= 0 ,0
Exp/Cntr=0.3,0.1

Type RM Length L Ch R = 1 ,1279.9  ,340.4,344.3,348.1
XS GIS Cut Line= 2
     1617484.053      293066.301     1617295.015      293367.735
#Sta/Elev= 26
       0     840     9.6  837.68    28.8  832.88    57.7     825    67.3   822.2
    76.9  819.24    86.6  815.99    96.2  811.67   105.8  806.53   115.4  800.87
     125  795.45   134.6  792.09   144.2   790.7   153.9  790.81   163.5  791.54
   173.1   792.3   182.7  792.88   221.2  794.73   269.3   796.8   278.9  797.26
   288.5  797.84   298.1   799.3   307.7  802.25   317.3  805.75   346.2  816.56
   355.8     820
#Mann= 3 , 0 , 0
       0     .06       0   134.6    .045       0   163.5     .06       0
Bank Sta=134.6,163.5
XS Rating Curve= 0 ,0
Exp/Cntr=0.3,0.1

Type RM Length L Ch R = 1 ,935.6   ,222.9,224,225
XS GIS Cut Line= 2
     1617306.781      292859.719     1616991.537      293216.022
#Sta/Elev= 30
       0     880    29.1  864.72    58.2  849.88    77.7  840.15    87.4  835.05
    97.1   829.7   106.8   824.9   116.5  821.07   126.2  818.06   145.6  812.87
     165  808.23   174.8  805.14   194.2  796.54   203.9  794.21     233   792.4
   252.4  791.61   262.1  791.44   291.3  791.34     301  790.44   310.9  788.19
   320.4  786.21   330.1  786.38   339.8  787.78   349.5  789.91   359.2  793.12
   368.9  797.69   388.4  808.17   407.8  818.07   446.6  836.61   475.7     850
#Mann= 3 , 0 , 0
       0     .06       0   310.9    .045       0   339.8     .06       0
Bank Sta=310.9,339.8
XS Rating Curve= 0 ,0
Exp/Cntr=0.3,0.1

Type RM Length L Ch R = 1 ,711.6   ,282.4,278.3,274.6
XS GIS Cut Line= 2
     1617177.607      292693.621     1616828.317      293052.753
#Sta/Elev= 30
       0     890    88.4  843.24    98.2  838.12     108  833.28   117.9  828.86
   127.7  825.07   137.5  821.76   176.8  809.24   186.6   806.3   196.5  803.77
   206.3  802.24   216.1   801.6   235.8  800.96   255.4  800.02   314.3  796.28
   324.2  794.24     334  789.36   343.8  784.62   353.6  783.18   363.4  783.64
   373.3  785.41   383.1  789.83   392.9  795.68   422.4  814.33   432.2  820.46
     442  826.44   451.9  831.96   471.5   842.5   491.2  854.05     501     860
#Mann= 3 , 0 , 0
       0      .1       0   343.8    .045       0   363.4      .1       0
Bank Sta=343.8,363.4
XS Rating Curve= 0 ,0
Exp/Cntr=0.3,0.1

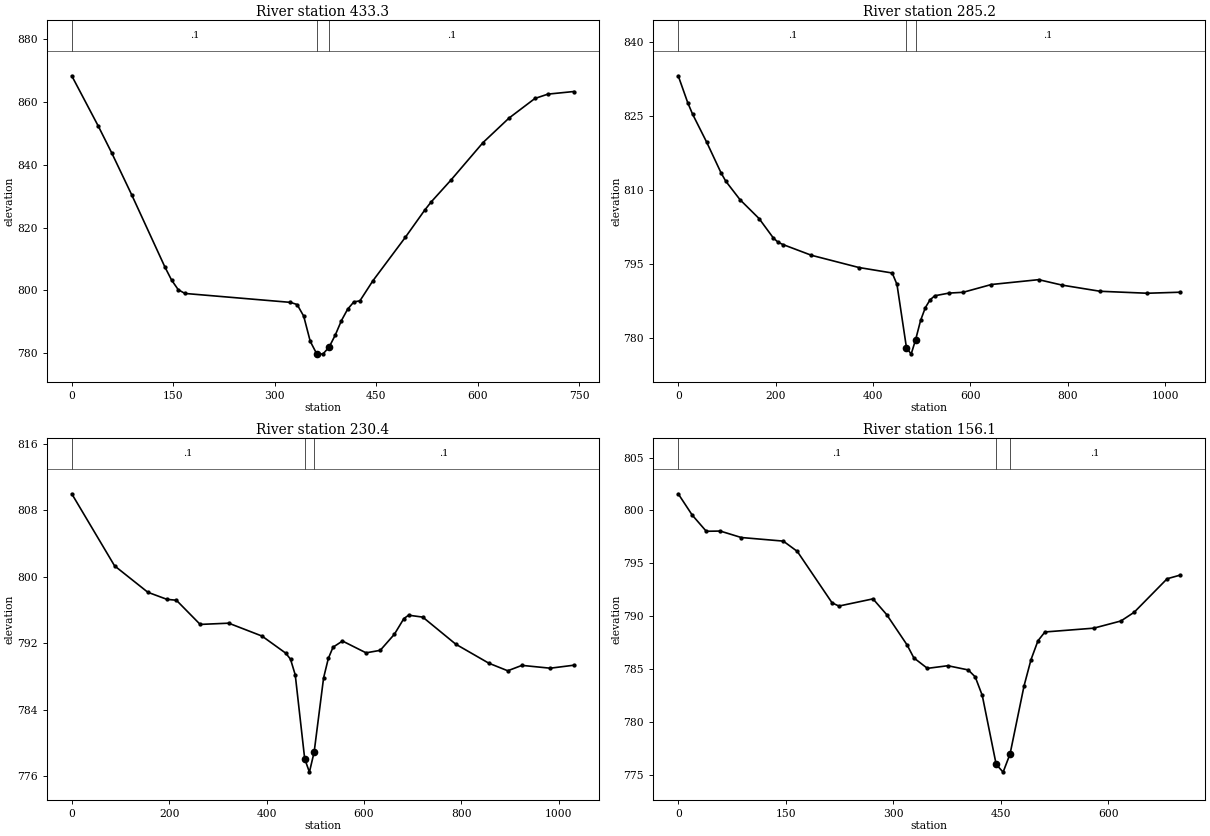
Type RM Length L Ch R = 1 ,433.3   ,147.1,148.1,148.4
XS GIS Cut Line= 5
     1616944.073      292508.602     1616809.588       292638.17
     1616712.286      292784.023     1616675.648      292836.026
     1616741.267       293145.13
#Sta/Elev= 30
       0  868.25    39.3   852.2      59  843.74    88.5  830.42   137.6  807.44
   147.4  803.31   157.3  800.23   167.1  799.04   323.1   796.2   332.9  795.51
   342.6  791.84   352.3   783.8   362.1  779.74   371.2   779.8   380.2  781.99
   389.3  785.82   398.4  790.42   407.5  794.02   416.6  796.33   425.7   796.7
   444.8  803.06   492.7  816.87   521.4  825.54     531  828.16   559.8  835.01
   607.6  847.04   645.9  854.81   684.2  861.05   703.4  862.43   741.7  863.26
#Mann= 3 , 0 , 0
       0      .1       0   362.1    .045       0   380.2      .1       0
Bank Sta=362.1,380.2
XS Rating Curve= 0 ,0
Exp/Cntr=0.3,0.1

Type RM Length L Ch R = 1 ,285.2   ,54.6,54.8,54.6
XS GIS Cut Line= 3
     1616874.567      292336.606     1616598.826      292691.087
     1616255.028      293160.371
#Sta/Elev= 30
       0  833.14    19.5   827.7    29.3  825.41    58.6  819.66    87.9  813.49
    97.6   811.8   126.9  808.05     166  804.23   195.3   800.3     205  799.44
   214.8  798.98   273.4   796.8     371  794.32   439.3  793.21   449.1  790.89
   468.5  778.12   478.2  776.78   487.4  779.72   497.6  783.61   507.3  786.19
     517  787.77   526.7   788.6   555.8  789.14   584.8   789.3     643  790.88
     740  791.86   788.4  790.75     866  789.51     963  789.11  1030.8  789.32
#Mann= 3 , 0 , 0
       0      .1       0   468.5    .045       0   487.4      .1       0
Bank Sta=468.5,487.4
XS Rating Curve= 0 ,0
Exp/Cntr=0.3,0.1

Type RM Length L Ch R = 1 ,230.4   ,73.2,74.3,75.4
XS GIS Cut Line= 3
     1616835.505      292297.544     1616559.763      292652.024
     1616215.966      293121.309
#Sta/Elev= 30
       0  809.97    87.9   801.3   156.2  798.12   195.3  797.27   214.8  797.16
   263.6  794.25   322.2   794.4   390.5  792.85   439.3  790.79   449.1  790.06
   458.8  788.18   478.2  778.08   487.9  776.47   497.6  778.88     517  787.81
   526.7  790.15   536.4  791.51   555.8  792.25   604.2  790.83   633.3  791.13
   662.4  793.07   681.8  794.95   691.5  795.36   720.6  795.13   788.4  791.87
   856.3  789.58   895.1  788.67   924.2  789.32   982.4  788.98  1030.8  789.34
#Mann= 3 , 0 , 0
       0      .1       0   478.2    .045       0   497.6      .1       0
Bank Sta=478.2,497.6
XS Rating Curve= 0 ,0
Exp/Cntr=0.3,0.1

Type RM Length L Ch R = 1 ,156.1   ,162.7,156.1,149.6
XS GIS Cut Line= 5
     1616793.054      292333.122     1616666.695      292494.695
     1616503.051      292608.625     1616380.835       292759.84
     1616358.313      292858.549
#Sta/Elev= 30
       0  801.57    19.5  799.56    39.1  798.03    58.6  798.05    87.9  797.44
   146.5   797.1     166  796.13   214.6  791.26   224.1  790.96   271.6  791.64
   290.6  790.16   319.1  787.29   328.6  786.06   347.5  785.07     376  785.32
   404.5  784.92   414.2  784.26     424  782.51   443.4  775.99   453.1  775.26
   462.8  776.99   482.3  783.42     492   785.9   501.7  787.68   511.4  788.51
   579.5  788.87   617.4  789.55   635.8  790.37   681.8  793.54   700.2  793.89
#Mann= 3 , 0 , 0
       0      .1       0   443.4    .045       0   462.8      .1       0
Bank Sta=443.4,462.8
XS Rating Curve= 0 ,0
Exp/Cntr=0.3,0.1

Chan Stop Cuts=-1
Use User Specified Reach Order=0
Composite Channel Slope=5